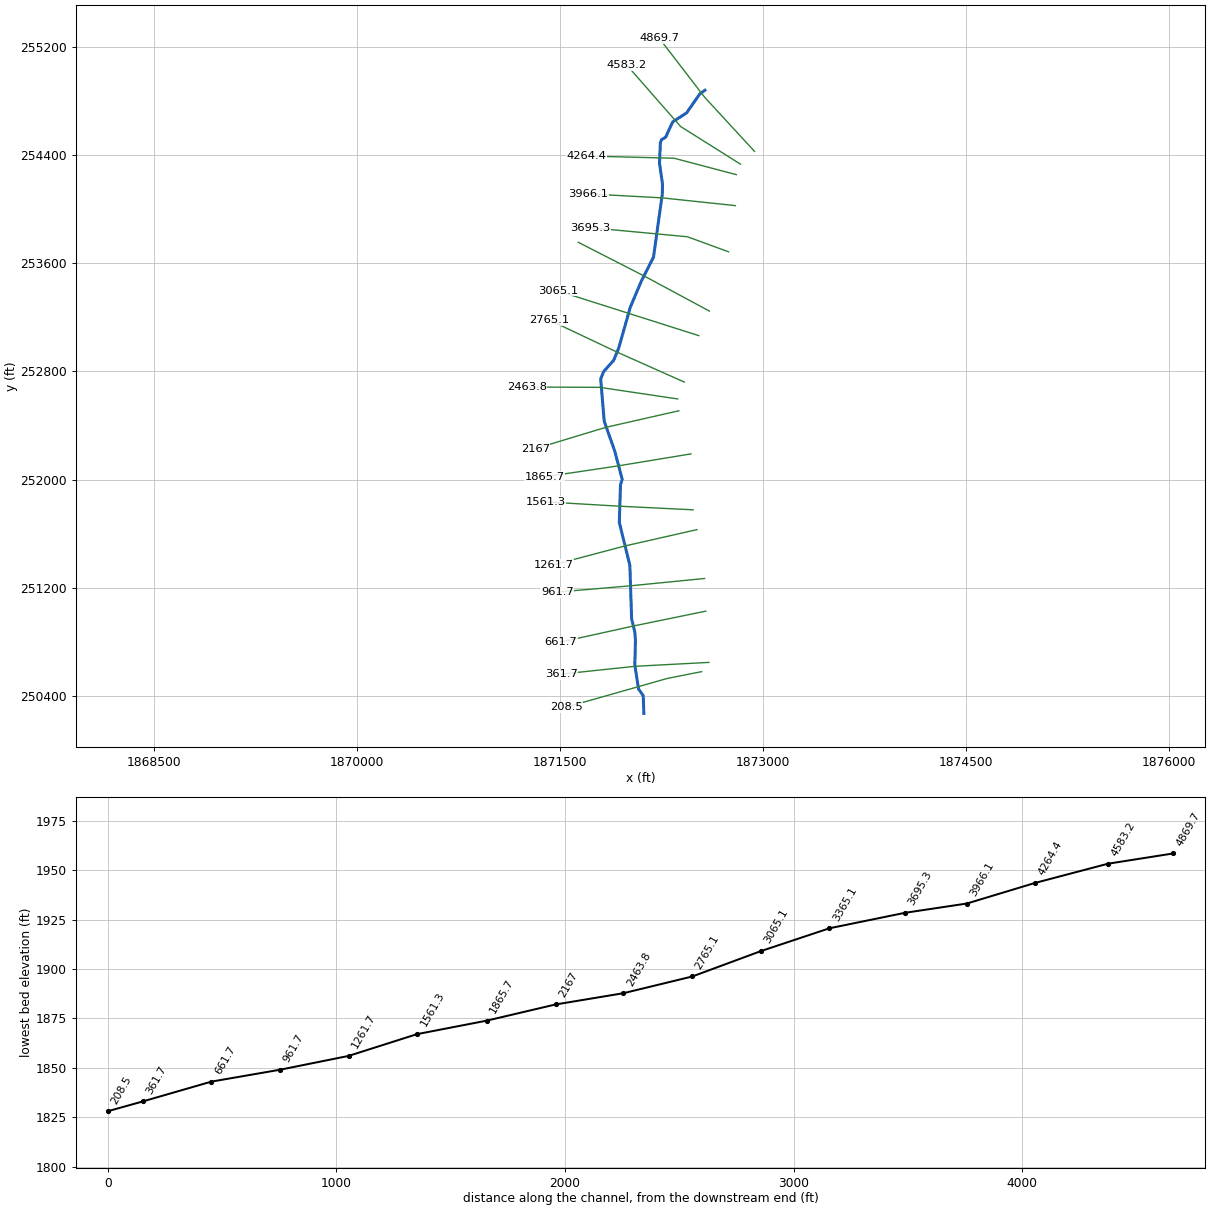
--- LwGpBrnch.prj (project) ---

Proj Title=LwGpBrnch
Current Plan=p01
Default Exp/Contr=0,0
English Units
Geom File=g01
Flow File=f01
Plan File=p01
BEGIN DESCRIPTION:
END DESCRIPTION:
DSS Export Rating Curves= 0
DSS Export Rating Curve Sorted= 0
DSS Export Volume Flow Curves= 0
DXF OffsetX= 0
DXF OffsetY= 0
DXF ScaleX= 0
DXF ScaleY= 0

--- LwGpBrnch.p01 (plan) ---

Plan Title=Floodplain
Program Version=4.00
Geom File=g01
Flow File=f01
K Sum by GR=0
Std Step Tol=0.01
Critical Tol=0.01
Num of Std Step Trials=20
Max Error Tol=0.3
Flow Tol Ratio=0.001
Split Flow NTrial=30
Split Flow Tol=0.02
Split Flow Ratio=0.02
Log Output Level=0
Friction Slope Method=1
Unsteady Friction Slope Method=2
Unsteady Bridges Friction Slope Method=1
Global Log Level=0
CheckData=False
Run HTab=0
Run UNet=0
Run PostProcess=0
UNET Theta=0
UNET Theta Warmup=0
UNET ZTol=0
UNET ZSATol=0
UNET MxIter=0
UNET MaxInSteps=0
UNET DtIC=0
UNET DtMin=0
UNET MaxCRTS=0
UNET WFStab=0
UNET SFStab=0
UNET WFX=0
UNET SFX=0
UNET DSS MLevel=0
UNET DZMax Abort=0
UNET Convert EG Bridges=0
UNET Use Existing IB Tables=0
UNET Froude Limit=0
UNET Froude Power=0
Write IC File=0
Echo Input=False
Echo Output=False
Write Detailed=0

--- LwGpBrnch.f01 (steady flow) ---

Flow Title=NFF Regression Equation
Program Version=4.00
Number of Profiles=1
Profile Names=P100yr
River Rch & RM=LwGpBrnch,Main      ,4869.7
903.6022
River Rch & RM=LwGpBrnch,Main      ,3966.1
930.1523
River Rch & RM=LwGpBrnch,Main      ,208.5
1018.951
Boundary for River Rch & Prof#=LwGpBrnch,Main      ,1
Up Type=0
Dn Type=3
Dn Slope=0.02861

--- LwGpBrnch.g01 (geometry) ---

Geom Title=USGS 3m DEM
Program Version=4.10

River Reach=LwGpBrnch       ,Main
Reach XY= 30
     1872570.789      254881.225     1872531.792      254852.986
     1872434.599       254712.91     1872332.665      254647.651
     1872279.936      254533.221     1872249.297      254514.795
     1872241.481      254493.955     1872234.962      254340.255
       1872257.1      254187.857     1872255.794      254113.612
     1872190.649      253646.003     1872102.069      253471.465
     1872019.588      253276.206      1871932.72      252969.994
     1871896.297       252882.37     1871821.923      252798.669
      1871800.78      252744.217     1871826.735        252431.9
     1871904.068      252212.001     1871959.504      252002.219
     1871946.878      251961.184     1871938.121      251682.646
     1872016.019      251366.562     1872029.028      250969.286
     1872052.693      250872.297     1872057.357      250808.941
     1872052.753      250628.421     1872080.124       250450.36
     1872114.836      250400.636     1872119.536       250269.97

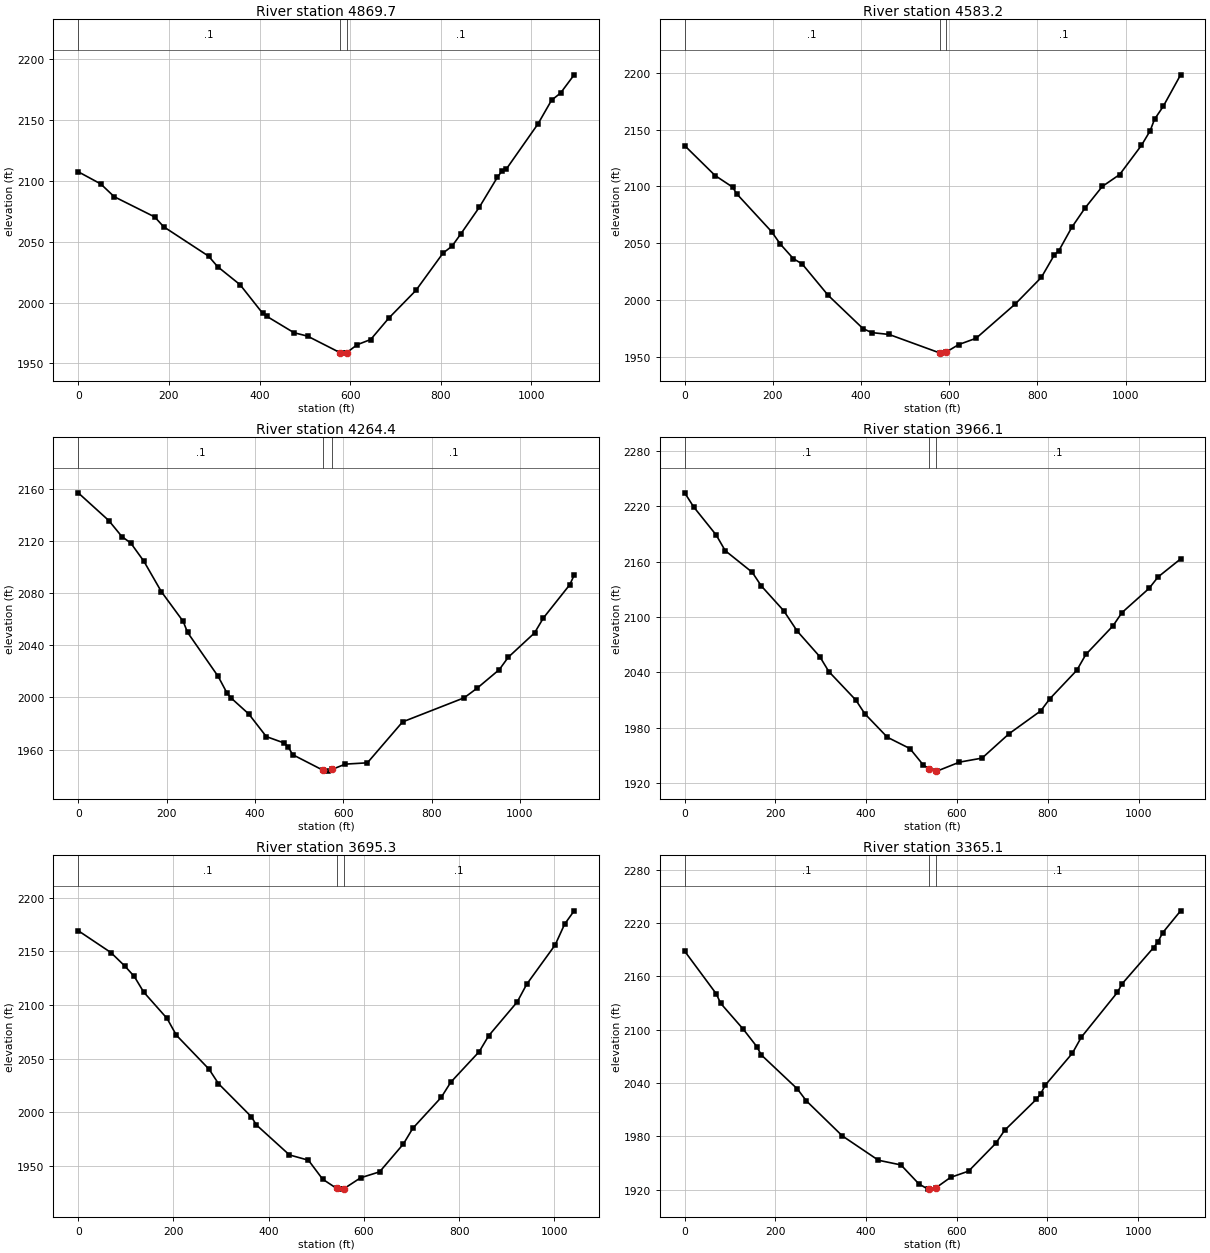
Type RM Length L Ch R = 1 ,4869.7  ,286,286.5,294.4
XS GIS Cut Line= 3
     1872936.948      254428.416     1872567.735      254830.027
     1872233.778      255265.308
#Sta/Elev= 30
       0 2107.47    49.6  2097.5    79.4 2086.98   168.6 2070.39   188.5  2062.3
   287.6 2038.15   307.5 2029.53   357.1 2014.69   406.7 1991.32   416.6  1988.6
   476.1 1975.24   505.9 1972.46   577.7 1958.86   585.4 1958.48   592.7 1958.98
   615.4 1965.37   645.3 1969.67   685.2 1987.23     745 2009.97   804.9 2040.66
   824.8 2046.37   844.8 2056.75   884.7 2078.16   924.6  2102.8   934.6 2107.94
   944.5 2109.66  1014.4 2146.78  1044.3 2166.23  1064.2 2172.14  1094.2  2187.1
#Mann= 3 , 0 , 0
       0      .1       0   577.7    .045       0   592.7      .1       0
Bank Sta=577.7,592.7
XS Rating Curve= 0 ,0
Exp/Cntr=0.3,0.1

Type RM Length L Ch R = 1 ,4583.2  ,299.5,318.8,338.1
XS GIS Cut Line= 3
     1872833.078      254334.097     1872390.738      254612.847
      1871994.56       255066.19
#Sta/Elev= 30
       0 2135.93      69 2109.62   108.5 2099.49   118.4 2093.35   197.3 2060.14
     217 2049.22   246.6 2036.39   266.4 2031.81   325.5 2004.14   404.5 1974.84
   424.2 1971.34   463.6  1969.7     578  1953.5   582.1 1953.26     593 1954.17
   621.5 1960.79     661 1966.34   749.8  1996.5   809.1 2019.99   838.7  2039.9
   848.6 2043.37   878.2 2064.09   907.8 2080.86   947.2 2099.99   986.7 2110.52
  1036.1  2136.2  1055.8 2149.01  1065.7 2159.14  1085.4 2170.46  1124.9 2198.28
#Mann= 3 , 0 , 0
       0      .1       0     578    .045       0     593      .1       0
Bank Sta=578,593
XS Rating Curve= 0 ,0
Exp/Cntr=0.3,0.1

Type RM Length L Ch R = 1 ,4264.4  ,300.1,298.3,297.6
XS GIS Cut Line= 3
     1872802.425      254256.543     1872342.796      254378.072
     1871695.419      254394.501
#Sta/Elev= 30
       0  2156.9    69.3 2135.63      99 2123.31   118.9 2118.45   148.6  2104.5
   188.2 2081.17   237.7 2058.33   247.6  2049.9     317  2016.1   336.8 2003.48
   346.7 1999.45   386.3 1987.32   425.9 1970.03   465.5 1965.22   475.4 1962.26
   485.4 1956.21   555.1  1944.1   565.1 1943.55   575.8 1945.01   604.9 1948.92
   654.8 1949.92   734.5 1981.29   873.9 1999.76   903.8 2007.26   953.6 2021.41
   973.6 2030.79  1033.3  2049.5  1053.3 2060.94    1113 2086.41    1123 2093.77
#Mann= 3 , 0 , 0
       0      .1       0   555.1    .045       0   575.8      .1       0
Bank Sta=555.1,575.8
XS Rating Curve= 0 ,0
Exp/Cntr=0.3,0.1

Type RM Length L Ch R = 1 ,3966.1  ,270.5,270.8,269.9
XS GIS Cut Line= 3
     1872795.558      254027.366     1872252.749      254084.862
     1871706.675      254114.465
#Sta/Elev= 30
       0 2234.34    19.8 2219.09    69.5 2188.64    89.3 2171.74   148.9 2148.32
   168.7 2133.64   218.3 2106.68   248.1 2084.58   297.7 2057.04   317.6 2040.88
   377.1 2010.03     397 1995.15   446.6 1969.79   496.2 1957.56     526 1939.62
   538.3 1935.68   553.3 1933.42   555.8 1933.13   605.5 1942.87   655.2 1947.22
   714.9 1973.69   784.5 1998.34   804.4 2011.38     864  2042.3   883.9 2059.41
   943.6  2090.3   963.5 2104.71  1023.1 2130.87    1043 2143.28  1092.7  2162.8
#Mann= 3 , 0 , 0
       0      .1       0   538.3    .045       0   553.3      .1       0
Bank Sta=538.3,553.3
XS Rating Curve= 0 ,0
Exp/Cntr=0.3,0.1

Type RM Length L Ch R = 1 ,3695.3  ,339.3,330.2,321.6
XS GIS Cut Line= 3
      1872745.22      253685.388      1872441.03      253797.008
     1871726.598      253863.751
#Sta/Elev= 30
       0  2169.2    68.7 2148.81    98.2 2136.13   117.8 2126.53   137.5 2112.02
   186.6 2087.44   206.2  2071.8   274.9 2040.11   294.6 2026.67   363.9 1995.77
   373.8  1988.4   443.6  1960.3   483.5 1955.37   513.4 1937.68   543.1 1929.02
   553.2 1928.43   558.1 1928.85   593.1 1938.98     633 1944.54   682.8  1970.4
   702.7 1985.08   762.5 2013.95   782.4    2028   842.2 2056.51   862.2 2071.38
     922  2102.8   941.9 2119.28  1001.7 2155.92  1021.6 2175.31  1041.6  2187.7
#Mann= 3 , 0 , 0
       0      .1       0   543.1    .045       0   558.1      .1       0
Bank Sta=543.1,558.1
XS Rating Curve= 0 ,0
Exp/Cntr=0.3,0.1

Type RM Length L Ch R = 1 ,3365.1  ,295.8,300,303.7
XS GIS Cut Line= 3
     1872603.702      253246.839     1872122.696      253506.042
     1871635.816      253755.782
#Sta/Elev= 30
       0 2188.18    69.5  2140.3    79.5 2129.45   129.2 2100.43     159 2080.91
   168.9 2071.54   248.4 2033.32   268.2 2019.91   347.7 1980.43   427.2 1953.09
   476.9 1947.81   516.6  1926.4   536.5 1920.61   538.9 1920.62   553.9 1922.06
   586.2 1933.79     626 1940.83   685.7 1971.96   705.6 1986.78   775.2 2021.45
   785.2  2027.9   795.1 2037.48   854.8 2073.35   874.7 2091.48   954.3 2141.91
   964.3 2151.32  1033.9 2192.13  1043.8 2198.69  1053.8 2208.74  1093.6 2233.54
#Mann= 3 , 0 , 0
       0      .1       0   538.9    .045       0   553.9      .1       0
Bank Sta=538.9,553.9
XS Rating Curve= 0 ,0
Exp/Cntr=0.3,0.1

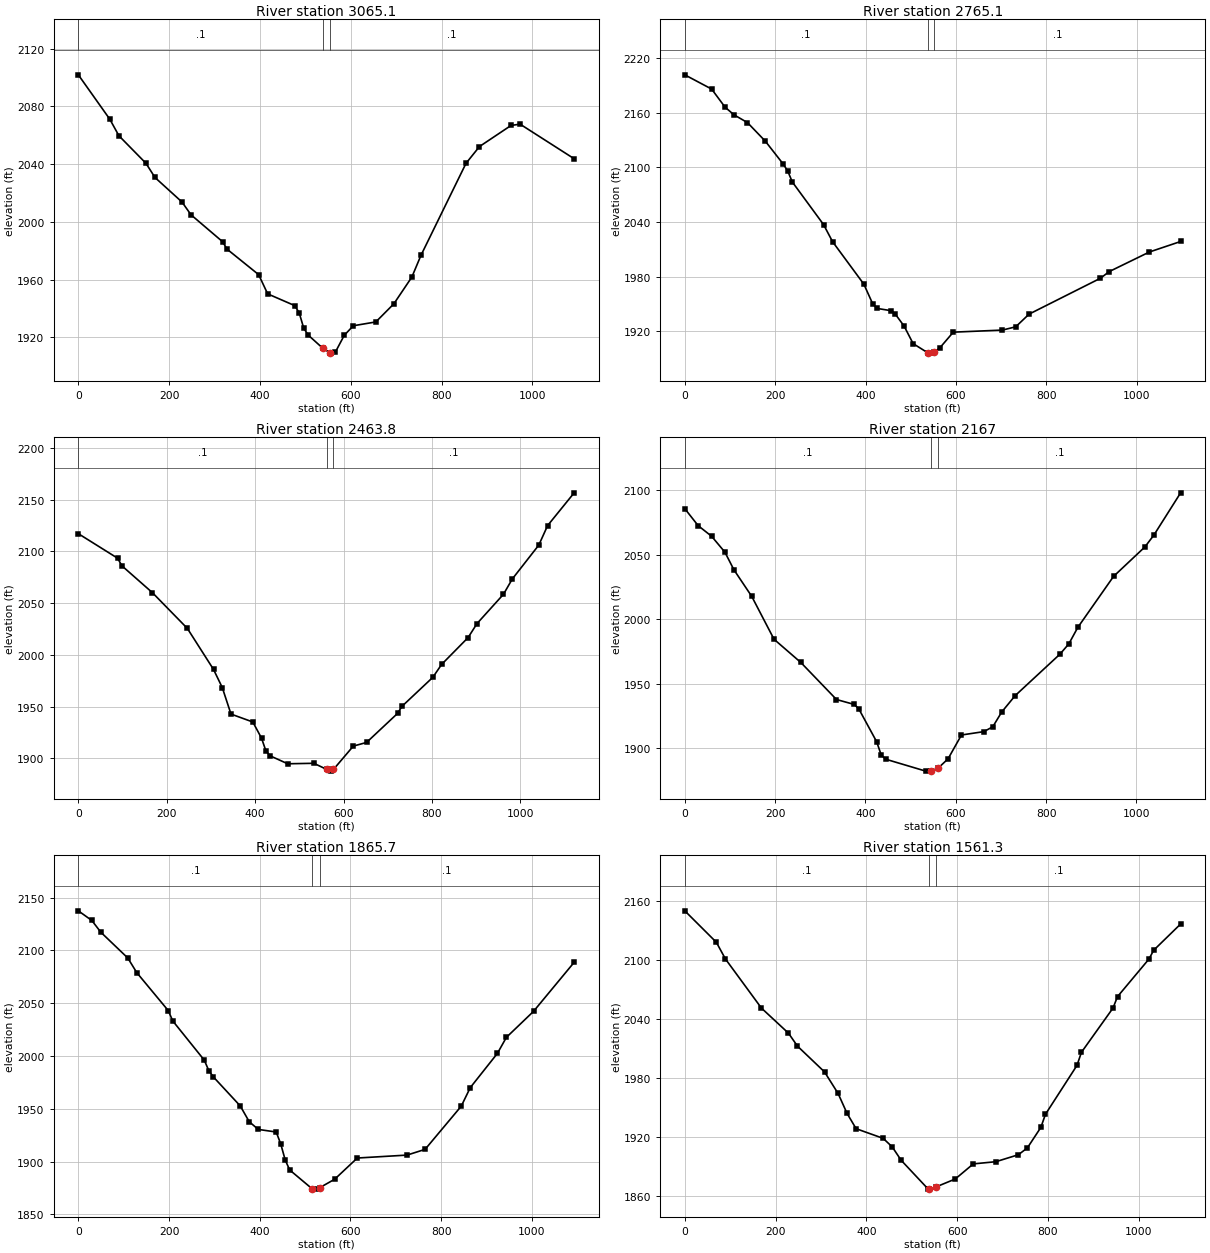
Type RM Length L Ch R = 1 ,3065.1  ,302.5,300,297
XS GIS Cut Line= 3
     1872525.396      253065.152     1872005.132      253230.809
     1871484.869      253396.466
#Sta/Elev= 30
       0  2101.9    69.5 2071.05    89.4 2059.67   148.9 2040.61   168.8 2030.77
   228.3 2013.76   248.2  2004.9   317.7 1986.26   327.6 1981.08   397.1 1963.45
     417 1950.12   476.5    1942   486.4    1937   496.4 1926.37   506.3 1921.55
   538.5 1912.42   553.5 1909.38   555.9 1909.06   565.8 1909.59   585.7 1921.43
   605.6 1928.03   655.2 1930.67   694.9 1943.23   734.6 1961.79   754.5 1976.75
   853.8 2040.57   883.5 2052.21     953 2066.82   972.9 2067.72    1092 2043.75
#Mann= 3 , 0 , 0
       0      .1       0   538.5    .045       0   553.5      .1       0
Bank Sta=538.5,553.5
XS Rating Curve= 0 ,0
Exp/Cntr=0.3,0.1

Type RM Length L Ch R = 1 ,2765.1  ,295.1,301.1,309.3
XS GIS Cut Line= 3
     1872418.229       252721.67     1871920.613      252943.769
      1871421.53      253180.434
#Sta/Elev= 30
       0 2201.73    59.4 2186.09    89.2 2166.17     109 2157.79   138.7 2149.28
   178.3 2128.84     218 2103.64   227.9 2096.03   237.8  2084.2   307.1 2037.32
     327 2018.58   396.3  1971.9   416.1 1950.06     426 1945.27   455.8 1942.87
   465.7 1939.16   485.5 1925.77   505.3 1906.65   537.4 1896.69   544.9 1896.22
   552.4 1897.32   564.7 1902.17   594.2 1919.24   702.8 1921.52   732.3 1925.09
   761.9 1939.03   919.7 1978.39   939.5 1985.79  1028.2 2007.24  1097.3 2018.77
#Mann= 3 , 0 , 0
       0      .1       0   537.4    .045       0   552.4      .1       0
Bank Sta=537.4,552.4
XS Rating Curve= 0 ,0
Exp/Cntr=0.3,0.1

Type RM Length L Ch R = 1 ,2463.8  ,288.4,296.9,305.3
XS GIS Cut Line= 3
     1872369.431      252596.835     1871793.512      252682.595
     1871253.918      252684.927
#Sta/Elev= 30
       0 2117.13    88.8 2093.44    98.7 2086.05   167.8 2060.08   246.7 2025.61
   305.9 1985.99   325.7 1968.49   345.4 1942.88   394.8 1935.24   414.5 1919.65
   424.4 1907.29   434.2 1902.51   473.7 1894.87   532.9 1895.34   562.2 1889.41
   572.4 1887.77   577.2 1889.37   622.2 1911.95   652.2 1915.48   722.2 1943.48
   732.2 1950.32   802.1 1978.37   822.1 1990.89     882 2016.82     902 2030.25
     962 2058.62     982 2073.42  1041.9 2106.11  1061.9    2125  1121.9 2156.59
#Mann= 3 , 0 , 0
       0      .1       0   562.2    .045       0   577.2      .1       0
Bank Sta=562.2,577.2
XS Rating Curve= 0 ,0
Exp/Cntr=0.3,0.1

Type RM Length L Ch R = 1 ,2167    ,302.6,301.3,298.1
XS GIS Cut Line= 3
       1872377.8      252509.232     1871838.359      252386.499
     1871317.107      252228.379
#Sta/Elev= 30
       0 2085.67    29.6 2072.49    59.3 2064.28    88.9 2051.89   108.7 2038.29
   148.2 2017.64   197.6 1984.36   256.9 1966.37   335.9 1937.61   375.4 1933.78
   385.3 1930.35   424.8  1904.9   434.7 1894.82   444.6 1891.34   533.5 1882.07
   545.7 1882.31   560.7 1884.31   582.9  1891.6   612.6  1910.1   662.2 1912.71
     682 1916.49   701.8 1927.95   731.5 1940.62   830.5 1972.74   850.3 1980.75
   870.2 1993.54   949.4 2033.13  1018.7 2055.96  1038.5 2065.06  1097.9 2097.96
#Mann= 3 , 0 , 0
       0      .1       0   545.7    .045       0   560.7      .1       0
Bank Sta=545.7,560.7
XS Rating Curve= 0 ,0
Exp/Cntr=0.3,0.1

Type RM Length L Ch R = 1 ,1865.7  ,309.3,304.4,299.5
XS GIS Cut Line= 3
     1872467.307       252190.22     1871929.183      252101.375
     1871387.283      252020.423
#Sta/Elev= 30
       0 2137.58    29.8 2128.42    49.6 2117.31   109.1 2092.86   128.9 2078.99
   198.3 2043.03   208.2 2033.26   277.7 1996.09   287.6 1986.26   297.5 1980.32
     357 1952.72   376.8 1937.79   396.7 1930.45   436.3    1928   446.2 1916.84
   456.2 1901.44   466.1 1892.01   515.7 1874.14   525.6 1873.88   531.9 1875.15
   565.3 1883.28   615.1 1903.35   724.7 1906.12   764.6 1911.55   844.3 1952.46
   864.2 1970.04     924 2002.47   943.9  2017.7  1003.7 2042.31  1093.3  2088.8
#Mann= 3 , 0 , 0
       0      .1       0   515.7    .045       0   531.9      .1       0
Bank Sta=515.7,531.9
XS Rating Curve= 0 ,0
Exp/Cntr=0.3,0.1

Type RM Length L Ch R = 1 ,1561.3  ,293.3,299.5,306.6
XS GIS Cut Line= 3
     1872483.597      251776.404     1871938.224      251803.167
     1871393.163      251835.081
#Sta/Elev= 30
       0 2150.34    69.5 2118.33    89.4  2101.4   168.8 2051.33   228.3 2025.82
   248.2  2012.6   307.8 1986.34   337.6 1964.44   357.4 1944.11   377.3 1928.58
   436.8 1918.76   456.7 1910.14   476.5 1896.45   536.1 1867.07   538.5 1867.09
   553.5 1869.35   595.7 1877.39   635.4 1892.76     685 1894.98   734.6 1902.07
   754.5 1909.04   784.3 1929.99   794.2 1943.17   863.7 1992.99   873.6 2006.38
   943.1  2051.4     953 2063.01  1022.5 2101.39  1032.5 2110.15    1092 2136.92
#Mann= 3 , 0 , 0
       0      .1       0   538.5    .045       0   553.5      .1       0
Bank Sta=538.5,553.5
XS Rating Curve= 0 ,0
Exp/Cntr=0.3,0.1

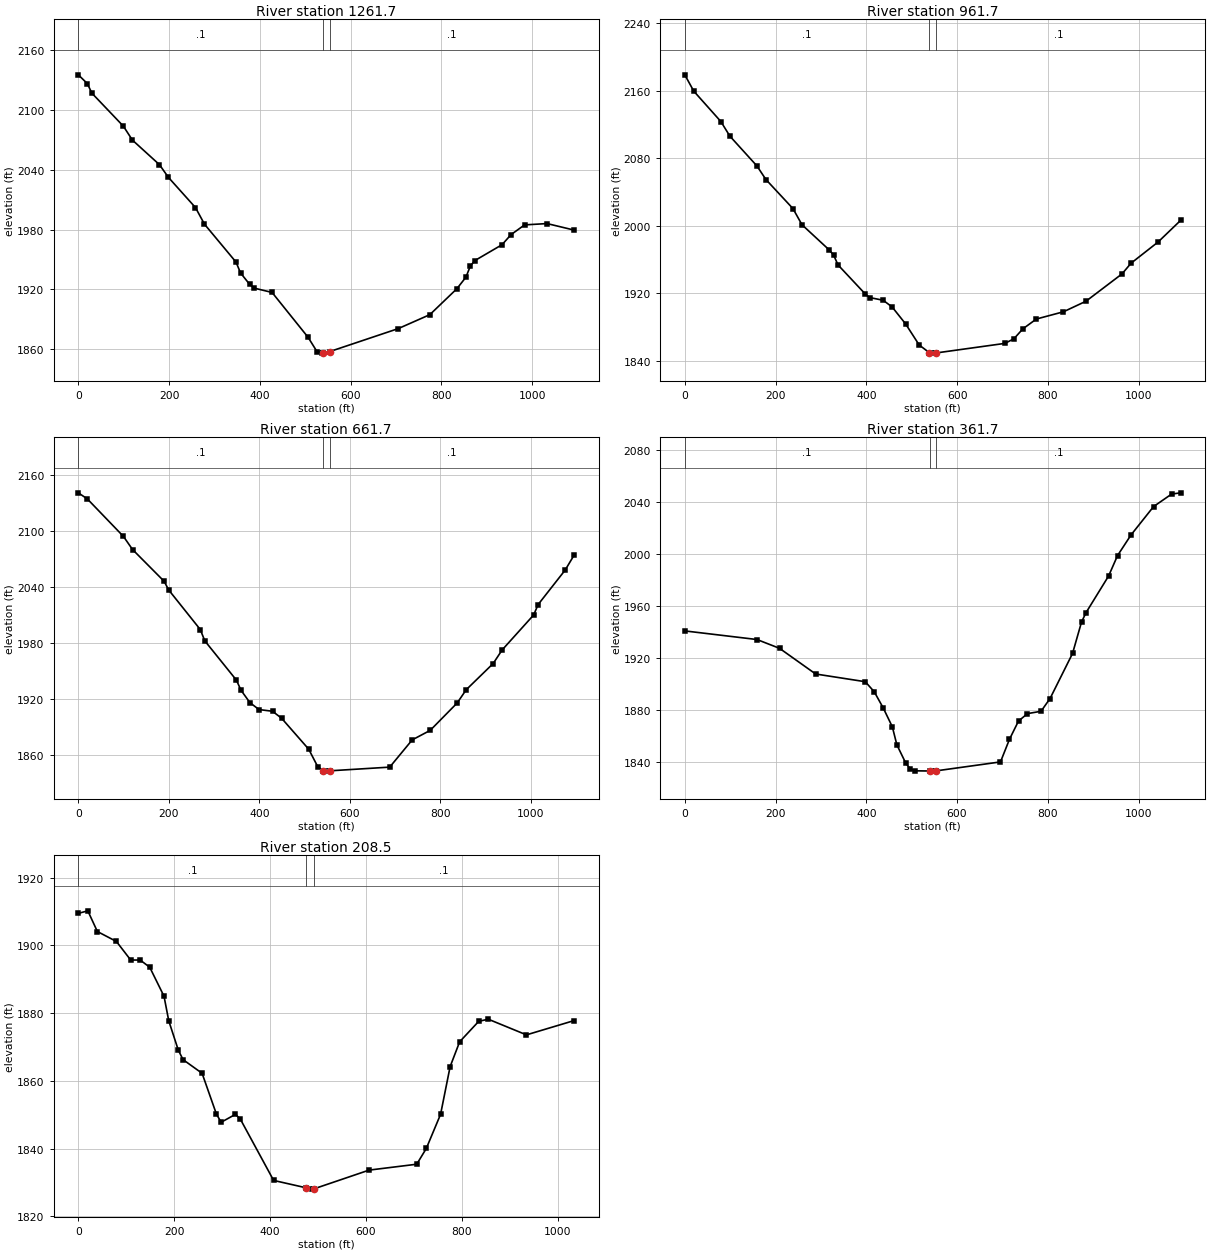
Type RM Length L Ch R = 1 ,1261.7  ,302.8,300,296.1
XS GIS Cut Line= 3
     1872511.926      251629.788     1871979.573      251508.806
     1871451.339      251369.042
#Sta/Elev= 30
       0 2135.41    19.8 2126.64    29.8 2117.02    99.3 2083.82   119.1  2069.9
   178.7 2045.22   198.5 2032.44   258.1 2002.14   277.9 1985.48   347.4 1947.41
   357.3 1936.58   377.2 1925.19   387.1 1921.33   426.8 1916.97   506.2 1871.91
   526.1 1857.32     536 1856.05   538.4 1856.19   553.4 1857.54   704.9 1880.69
   774.4 1894.67     834 1920.73   853.9 1932.32   863.8 1943.71   873.8 1949.02
   933.4 1964.88   953.2 1974.99   983.1 1984.78  1032.7 1986.09  1092.3 1979.54
#Mann= 3 , 0 , 0
       0      .1       0   538.4    .045       0   553.4      .1       0
Bank Sta=538.4,553.4
XS Rating Curve= 0 ,0
Exp/Cntr=0.3,0.1

Type RM Length L Ch R = 1 ,961.7   ,297.6,300,303
XS GIS Cut Line= 3
     1872567.701      251268.123     1872024.365      251214.348
     1871480.328      251167.462
#Sta/Elev= 30
       0 2178.83    19.8 2159.47    79.4 2123.51    99.3 2106.17   158.8  2070.9
   178.7 2054.74   238.2 2020.33   258.1 2001.19   317.7 1971.51   327.6  1965.4
   337.5 1953.55   397.1 1919.32     407 1914.92   436.8 1911.72   456.6 1903.77
   486.4 1883.61   516.2 1858.71   538.5 1849.64     546 1849.06   553.5 1849.27
   704.8 1860.59   724.7    1866   744.6 1877.85   774.3 1889.47   833.9 1898.04
   883.6 1910.57     963 1942.98   982.8  1955.6  1042.4 1980.74    1092 2006.36
#Mann= 3 , 0 , 0
       0      .1       0   538.5    .045       0   553.5      .1       0
Bank Sta=538.5,553.5
XS Rating Curve= 0 ,0
Exp/Cntr=0.3,0.1

Type RM Length L Ch R = 1 ,661.7   ,303.4,300,297.4
XS GIS Cut Line= 3
     1872576.278      251026.307     1872038.503       250915.76
     1871504.744      250797.358
#Sta/Elev= 30
       0 2141.41      20 2134.82    99.8  2094.6   119.8 2080.64   189.7 2046.52
   199.6 2037.34   269.5 1994.86   279.5 1982.72   349.4 1940.58   359.4 1929.85
   379.3 1916.44   399.3 1909.06   429.2 1907.22   449.2 1899.76   509.1 1866.59
   529.1 1847.82   541.5 1843.64     549 1843.05   556.5  1843.4   688.2 1847.34
   737.9 1876.55   777.6 1886.73   837.3 1916.14   857.2  1930.3   916.8 1958.41
   936.7 1973.01  1006.3 2010.48  1016.2 2021.67  1075.9 2058.59  1095.8  2074.7
#Mann= 3 , 0 , 0
       0      .1       0   541.5    .045       0   556.5      .1       0
Bank Sta=541.5,556.5
XS Rating Curve= 0 ,0
Exp/Cntr=0.3,0.1

Type RM Length L Ch R = 1 ,361.7   ,148.2,153.2,157.1
XS GIS Cut Line= 3
     1872599.974      250647.327     1872053.827      250618.305
     1871511.034      250560.725
#Sta/Elev= 30
       0 1940.73   159.1 1934.11   208.8 1927.36   288.4 1907.63   397.8 1901.71
   417.6 1893.95   437.5 1881.45   457.4 1867.06   467.4 1853.23   487.2 1839.02
   497.2 1834.57   507.1 1833.26   539.4 1833.13   546.9 1833.03   554.4 1833.26
   695.8 1840.11   715.6 1857.51   735.5 1871.51   755.3  1877.2   785.1    1879
     805 1888.78   854.6 1923.43   874.4 1947.57   884.4 1954.81     934 1982.88
   953.8 1998.62   983.6 2014.51  1033.2 2036.24  1072.9 2045.82  1092.8 2046.79
#Mann= 3 , 0 , 0
       0      .1       0   539.4    .045       0   554.4      .1       0
Bank Sta=539.4,554.4
XS Rating Curve= 0 ,0
Exp/Cntr=0.3,0.1

Type RM Length L Ch R = 1 ,208.5   ,214.1,208.5,202.8
XS GIS Cut Line= 3
     1872546.002      250578.774     1872292.817      250528.639
     1871546.494      250316.136
#Sta/Elev= 30
       0 1909.46    19.8 1910.21    39.7  1904.1    79.4 1901.17   109.2 1895.69
     129 1895.68   148.9 1893.56   178.7    1885   188.6 1877.74   208.5 1869.09
   218.4 1866.29   258.1 1862.26     288 1850.21   297.9 1847.81   327.7 1850.14
   337.7 1848.78   407.3 1830.64   475.7 1828.44   486.9 1828.07   490.7 1828.12
   606.3 1833.68   705.8 1835.42   725.7 1840.07   755.5 1850.15   775.4 1864.22
   795.3 1871.56   835.1  1877.6     855 1878.22   934.6  1873.6  1034.1 1877.82
#Mann= 3 , 0 , 0
       0      .1       0   475.7    .045       0   490.7      .1       0
Bank Sta=475.7,490.7
XS Rating Curve= 0 ,0
Exp/Cntr=0.3,0.1

Chan Stop Cuts=-1
Use User Specified Reach Order=0
Composite Channel Slope=5